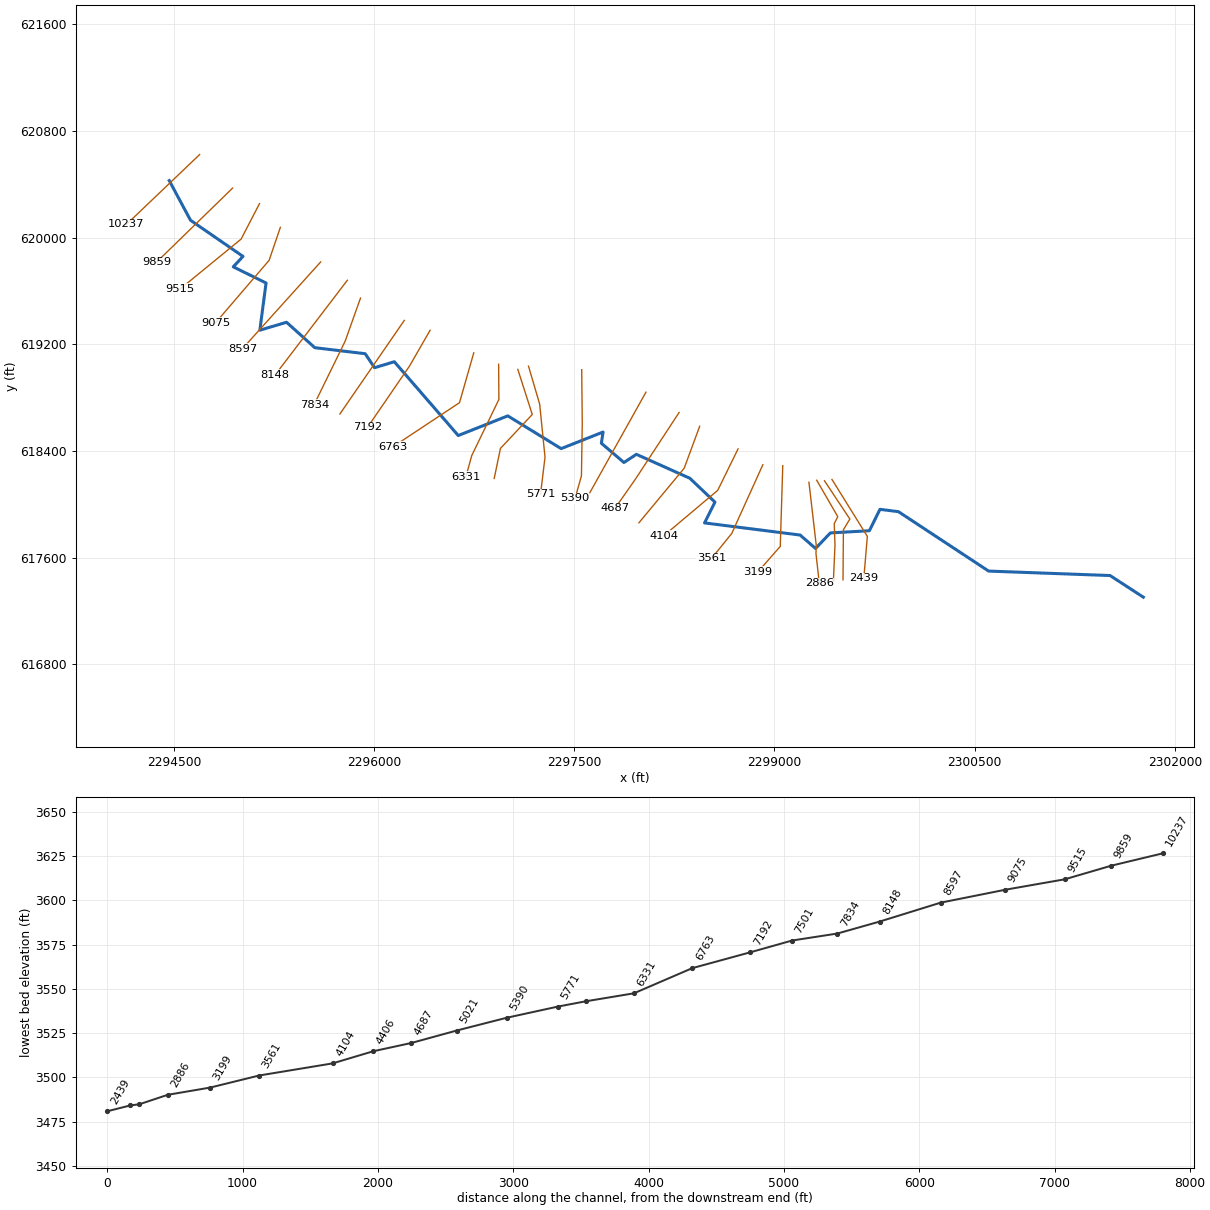
--- YOKUMRN.prj (project) ---

Proj Title=YOKUMRN
Current Plan=p01
Default Exp/Contr=0,0
English Units
Geom File=g01
Flow File=f01
Plan File=p01
BEGIN DESCRIPTION:
----------MODEL BY WOOD PLC 2022----------
AFH study
Randolph County, WV
HEC-RAS Version: RAS 6.2
Vertical Datum: NAVD88
Projection: NAD 1983 StatePlane West Virginia S FIPS 4702 (US Feet)
Terrain: 1-meter LIDAR (FEMA Region III 3DEP collected 2016-2018)
Land Use: 2019 NLCD
Hydrologic Method:
WV SIR2010-5033 regression equations
Additional Model Notes:
None
END DESCRIPTION:
DSS Export Rating Curves= 0
DSS Export Rating Curve Sorted= 0
DSS Export Volume Flow Curves= 0
DXF OffsetX= 0
DXF OffsetY= 0
DXF ScaleX= 0
DXF ScaleY= 0

--- YOKUMRN.p01 (plan) ---

Plan Title=Floodplain
Program Version=6.20
Short Identifier=Floodplain
Geom File=g01
Flow File=f01
Subcritical Flow
K Sum by GR= 0
Std Step Tol= 0.01
Critical Tol= 0.01
Num of Std Step Trials= 20
Max Error Tol= 0.3
Flow Tol Ratio= 0.001
Split Flow NTrial= 30
Split Flow Tol= 0.02
Split Flow Ratio= 0.02
Log Output Level= 0
Friction Slope Method= 1
Unsteady Friction Slope Method= 2
Unsteady Bridges Friction Slope Method= 1
Parabolic Critical Depth
Global Vel Dist= 0 , 0 , 0
Global Log Level= 0
CheckData=True
Encroach Param=-1 ,0,0, 0
Mapping Interval=1HOUR
Computation Time Step Use Courant=        0
Computation Time Step Use Time Series=    0
Computation Time Step Count To Double=0
Computation Time Step Max Doubling=0
Computation Time Step Max Halving=0
Computation Time Step Residence Courant=0
Run HTab= 0
Run UNet= 0
Run Sediment= 0
Run PostProcess= 0
Run WQNet= 0
Run RASMapper=-1
UNET Theta= 0
UNET Theta Warmup= 0
UNET ZTol= 0
UNET ZSATol= 0
UNET MxIter= 0
UNET Max Iter WO Improvement= 0
UNET MaxInSteps= 0
UNET DtIC= 0
UNET DtMin= 0
UNET MaxCRTS= 0
UNET WFStab= 0
UNET SFStab= 0
UNET WFX= 1
UNET SFX= 1
UNET Gravity=32.174
UNET 1D Methodology=Finite Difference
UNET DSS MLevel= 1
UNET Pardiso=0
UNET DZMax Abort= 0
UNET Use Existing IB Tables= 0
UNET Froude Reduction=False
UNET Froude Limit= 0
UNET Froude Power= 0
UNET D1 Cores= 0
UNET WindReference=Eulerian
UNET WindDragFormulation=Hsu (1988)
UNET D2 Coriolis=0
UNET D2 Cores= 0
UNET D2 Theta= 1
UNET D2 Theta Warmup= 1
UNET D2 Z Tol= 0.01
UNET D2 Volume Tol= 0.01
UNET D2 Max Iterations= 20
UNET D2 Equation= 0
UNET D2 RampUpFraction=0.1
UNET D2 TimeSlices= 1
UNET D2 Turbulence Formulation=Non-Conservative (original)
UNET D2 Eddy Viscosity=0.3
UNET D2 Transverse Eddy Viscosity=0.1
UNET D2 Smagorinsky Mixing=0
UNET D2 BCVolumeCheck=0
UNET D2 Cores=0
UNET D2 SolverType=PARDISO (Direct)
UNET D2 Minimum Iterations= 2147483647
UNET D2 Maximum Iterations= 2147483647
UNET D2 Restart Number= 10
UNET D2 Relaxation Coeff=1.3
UNET D2 SOR Precondition Iterations= 10
UNET D2 ILUT Maximum Fill= 8
UNET D2 ILUT Tolerance=1E-08
UNET D1D2 MaxIter= 0
UNET D1D2 ZTol=0.01
UNET D1D2 QTol=0.1
UNET D1D2 MinQTol=1
Write IC File= 0
Write IC File at Fixed DateTime=0
Write IC File at Sim End=0
Echo Input=False
Echo Parameters=False
Echo Output=False
Write Detailed= 0
HDF Write Warmup=0
HDF Write Time Slices=0
HDF Flush=0
HDF Compression= 1
HDF Chunk Size= 1
HDF Spatial Parts= 1
HDF Use Max Rows=0
HDF Fixed Rows= 1
Calibration Method= 0
Calibration Iterations= 20
Calibration Max Change=0.05
Calibration Tolerance=0.2
Calibration Maximum=1.5
Calibration Minimum=0.5
Calibration Optimization Method= 1
WQ AD Non Conservative
WQ ULTIMATE=-1
WQ Max Comp Step=1HOUR
WQ Output Interval=15MIN
WQ Output Selected Increments= 0
WQ Output face flow=0
WQ Output face velocity=0
WQ Output face area=0
WQ Output face dispersion=0
WQ Output cell volume=0
WQ Output cell surface area=0
WQ Output cell continuity=0
WQ Output cumulative cell continuity=0
WQ Output face conc=0
WQ Output face dconc_dx=0
WQ Output face courant=0
WQ Output face peclet=0
WQ Output face adv mass=0
WQ Output face disp mass=0
WQ Output cell mass=0
WQ Output cell source sink temp=0
WQ Output nsm pathways=0
WQ Output nsm derived pathways=0
WQ Create Restart=0
WQ Fixed Restart=0
WQ System Summary=0
WQ Write To DSS=0
Sorting and Armoring Iterations= 10
XS Update Threshold= 0.02
Bed Roughness Predictor= 0
Hydraulics Update Threshold= 0.02
Energy Slope Method= 1
Volume Change Method= 1
Sediment Retention Method= 0
Sediment TS Multiplier= 1
Warm Up Method= 0
XS Weighting Method= 0
Number of US Weighted Cross Sections= 1
Number of DS Weighted Cross Sections= 1
Upstream XS Weight=0
Main XS Weight=1
Downstream XS Weight=0
Number of DS XS's Weighted with US Boundary= 1
Upstream Boundary Weight= 1
Weight of XSs Associated with US Boundary= 0
Number of US XS's Weighted with DS Boundary= 1
Downstream Boundary Weight= 0.5
Weight of XSs Associated with DS Boundary= 0.5
Percentile Method= 0
Sediment Output Level= 3
Mass or Volume Output= 0
Output Increment Type= 1
Profile and TS Output Increment= 1
Transport Output Increment 1
XS Output Flag= 0
XS Output Increment= 10
Read HDF5 Sediment Hotstart= 0
Sediment Hotstart Type= 0
Write Gradation File= 0
Read Gradation Hotstart= 0
Write HDF5 File= 1
Write Binary Output= 1
Write DSS Sediment File= 0
DSS Sediment Output Type= 1
SV Curve= 0
Specific Gage Flag= 0
Subcell Erosion Methods= 0
Subcell Deposition Methods= 0
Advection Scheme= 1
Matrix Solver= 0
Implicit Weighting Factor= 1
Maximum Outer Loop Convergence Iterations= 5
Convergence Maximum Absolute= 0.001
Convergence RMSE= 0.0001
Grain Fractions Max Abs Error= 0.001
Max Subgrid Regions= 1
Max Subgrid Length Scale= 3.402823E+38
Initial Layer Thickness= 3.402823E+38
Min Layer Thickness= 3.402823E+38
Max Layer Thickness= 3.402823E+38
Number of Layers= 5

--- YOKUMRN.f01 (steady flow) ---

Flow Title=Flow
Program Version=6.20
Number of Profiles= 1
Profile Names=P100yr
River Rch & RM=YOKUMRN,Main            ,10237
     363
River Rch & RM=YOKUMRN,Main            ,6763
     409
River Rch & RM=YOKUMRN,Main            ,5390
     488
River Rch & RM=YOKUMRN,Main            ,2886
     560
Boundary for River Rch & Prof#=YOKUMRN,Main            , 1
Up Type= 0
Dn Type= 3
Dn Slope=0.03217
DSS Import GetInterval= 0
DSS Import GetPeak= 0
DSS Import FillOption= 0

--- YOKUMRN.g01 (geometry) ---

Geom Title=Geometry
Program Version=6.20

River Reach=YOKUMRN         ,Main
Reach XY= 30
     2294466.014       620426.61     2294625.345      620129.475
     2295018.357      619858.858     2294945.441      619780.516
       2295191.1       619659.64     2295144.659      619305.527
     2295344.746      619364.772     2295556.552      619174.234
     2295933.939      619129.095     2296004.251      619024.277
     2296152.255      619068.982     2296631.306      618515.691
     2297002.412      618663.006     2297402.239      618417.519
     2297716.475      618541.912     2297703.527      618457.884
     2297872.798       618313.44       2297966.2      618374.724
     2298366.548      618195.211     2298554.742      618016.391
     2298476.738      617860.523     2299193.145      617769.507
     2299308.379      617668.856     2299419.447      617785.523
     2299711.687      617801.889     2299791.375      617962.306
     2299929.708      617944.702     2300605.282      617499.363
     2301515.333      617465.952     2301764.636      617303.675

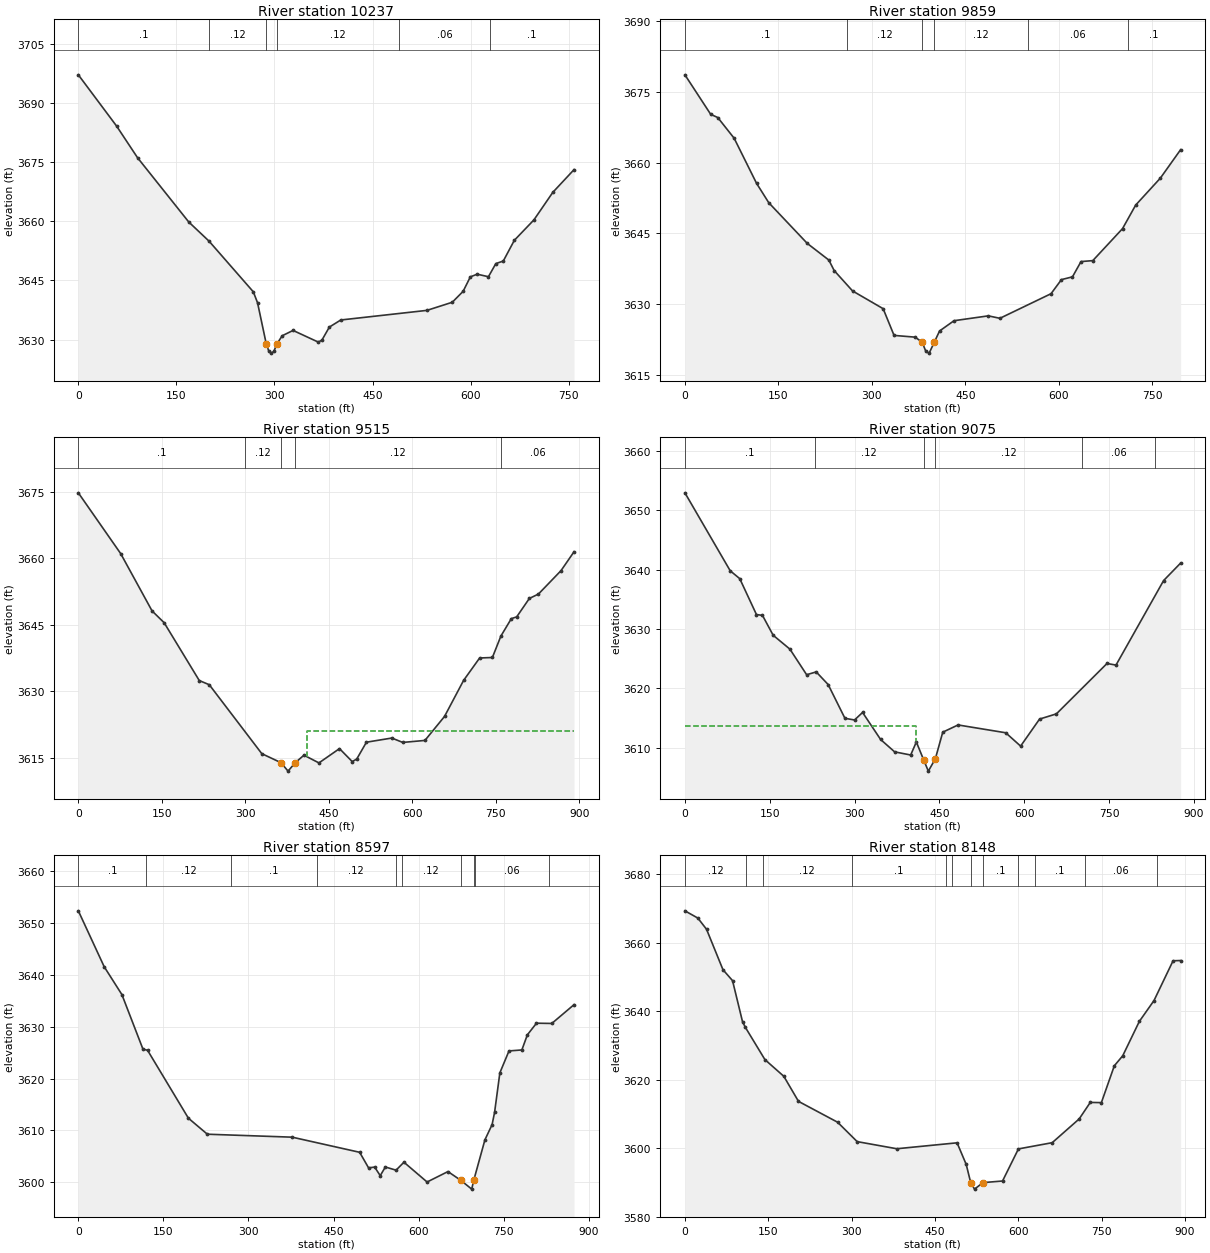
Type RM Length L Ch R = 1 ,10237   ,376.4,378.9,377.5
XS GIS Cut Line= 2
2294693.62357788620622.5217787822294145.54246175620098.749458991
#Sta/Elev= 30
       0 3697.17    58.6 3684.15    90.5 3676.15   168.9 3659.82     200 3654.95
   267.6 3642.11   274.1 3639.32  287.293628.987   291.4    3627   295.2 3626.55
     299 3626.99  303.963628.961   311.8 3630.96   328.4 3632.31   367.2 3629.33
   372.7  3629.9   383.9 3633.16   401.4 3634.96   533.2  3637.4   571.9 3639.46
   588.5 3642.24   599.5  3645.9   609.9 3646.58   627.2 3645.94   638.5 3649.27
   649.9 3649.92   666.8 3655.18   696.7 3660.35   725.6 3667.34   758.1 3673.12
#Mann= 6 ,-1,0
       0      .1       0     200     .12       0  287.29    .045       0
  303.96     .12       0     490     .06       0     630      .1       0
Bank Sta=287.29,303.96
XS Rating Curve= 0 ,0
Exp/Cntr=0.3,0.1

Type RM Length L Ch R = 1 ,9859    ,343.1,343.8,339.2
XS GIS Cut Line= 2
2294940.76538801620371.0816967652294371.26727464619816.118838725
#Sta/Elev= 30
       0 3678.67    41.4 3670.28    52.7 3669.61      79 3665.21   114.9 3655.65
   134.5 3651.53   196.3 3642.89   230.9 3639.36   239.4 3637.14   268.9 3632.81
     318 3629.04   335.5 3623.37   369.4    3623   380.6 3621.92   386.5 3619.98
   391.8 3619.61  399.893621.885   408.5 3624.31   431.7 3626.49   486.7 3627.52
   505.3    3627   587.3 3632.22     604 3635.21   621.7  3635.8   635.4 3639.04
   654.3 3639.24     702 3646.03   723.1 3651.03   762.7 3656.75   795.2 3662.79
#Mann= 6 ,-1,0
       0      .1       0     260     .12       0   380.6    .045       0
  399.89     .12       0     550     .06       0     710      .1       0
Bank Sta=380.6,399.89
XS Rating Curve= 0 ,0
Exp/Cntr=0.3,0.1

Type RM Length L Ch R = 1 ,9515    ,435,439.9,435.3
XS GIS Cut Line= 3
2295141.82947555620254.1110285922295004.30567124 619988.55123099
2294546.69296589  619613.7745696
#Sta/Elev= 30
       0 3674.84    76.1  3661.1   132.5 3648.14   154.2 3645.47   217.3  3632.4
   235.3 3631.45   329.6 3615.87   364.1 3613.83   376.8 3611.92   389.7 3613.83
   405.4 3615.52   432.3 3613.78   469.2 3617.01     492 3614.09   500.1 3614.63
   517.6 3618.46   563.2  3619.4   582.9 3618.41   622.7 3618.86   657.9 3624.28
   692.2 3632.44     721  3637.5   743.9 3637.61   759.2 3642.46   777.9 3646.39
   787.6  3646.8   810.3 3650.96   826.6 3651.95   867.2 3657.25   890.6 3661.52
#Mann= 5 ,-1,0
       0      .1       0  299.06     .12       0   364.1    .045       0
   389.7     .12       0  759.06     .06       0
#XS Ineff= 2 , 0
                          410.83          3621.1
Permanent Ineff=
       F       F
Bank Sta=364.1,389.7
XS Rating Curve= 0 ,0
Exp/Cntr=0.3,0.1

Type RM Length L Ch R = 1 ,9075    ,475.6,478,476.3
XS GIS Cut Line= 3
2295298.46105619620076.9725189342295214.12157512619829.271017554
2294813.77787835619362.338269125
#Sta/Elev= 30
       0 3652.97    80.1 3639.82      97 3638.49   126.5 3632.44   137.2 3632.29
   156.1 3628.94   185.7  3626.6   215.3 3622.28   232.2 3622.76   253.3 3620.63
     283 3614.93     300 3614.65   314.2 3615.92   346.1 3611.36   370.9 3609.27
   399.3 3608.74   409.3 3610.94     422 3607.97   430.5 3606.02   442.9  3608.1
     456 3612.59   483.1 3613.81   567.4 3612.49   593.7 3610.24   627.2  3614.8
     657 3615.68   746.5 3624.18   762.4 3623.91   846.6 3638.17   876.7 3641.12
#Mann= 6 ,-1,0
       0      .1       0     230     .12       0     422    .045       0
   442.9     .12       0  701.67     .06       0  831.67     .12       0
#XS Ineff= 2 , 0
          407.94 3613.55
Permanent Ineff=
       F       F
Bank Sta=422,442.9
XS Rating Curve= 0 ,0
Exp/Cntr=0.3,0.1

Type RM Length L Ch R = 1 ,8597    ,443.3,448.8,440.9
XS GIS Cut Line= 2
2295600.43042251619817.3683241992295015.40234577619167.987159013
#Sta/Elev= 30
       0 3652.28    45.6 3641.52    76.8 3636.16   113.9 3625.67   122.1 3625.43
   194.1 3612.36   227.5 3609.28   377.1 3608.71     496  3605.8   511.7 3602.81
   522.5 3602.95   532.3  3601.3   541.3 3602.97   560.2 3602.36   574.1 3603.89
   614.9 3600.08   651.7 3602.09   674.4  3600.4   693.6 3598.71   697.1 3600.38
   716.9 3608.21   729.5 3611.12   733.9 3613.48   743.2 3621.09   759.3 3625.31
     782  3625.5   791.7 3628.41   807.8 3630.65   834.8  3630.6     874 3634.22
#Mann= 10 ,-1,0
       0      .1       0     120     .12       0     270      .1       0
     420     .12       0     560      .1       0     570     .12       0
   674.4    .045       0   697.1     .12       0     700     .06       0
     830     .12       0
Bank Sta=674.4,697.1
XS Rating Curve= 0 ,0
Exp/Cntr(USF)=0,0
Exp/Cntr=0.3,0.1

Type RM Length L Ch R = 1 ,8148    ,310.6,314,314.5
XS GIS Cut Line= 2
2295800.14616024619679.6696912462295259.14293261618970.348180318
#Sta/Elev= 30
       0 3669.32    23.3  3667.2    38.9 3663.94    68.5 3652.12    85.7 3648.94
   103.7 3636.93   108.8  3635.3     144 3625.88     178 3621.01   204.4 3613.69
   274.8  3607.6     310 3601.94   381.3 3599.86   489.8 3601.59   506.2 3595.29
   514.4 3589.91   521.2 3588.07   536.4 3589.97   571.6 3590.44   600.2 3599.81
     661 3601.63   709.5 3608.56   729.5 3613.38   749.5 3613.33   772.8 3624.09
   787.9    3627   817.8 3637.04   844.2 3643.13   878.5 3654.74   892.1 3654.81
#Mann= 12 ,-1,0
       0     .12       0     110      .1       0     140     .12       0
     300      .1       0     470     .12       0     480      .1       0
   514.4    .045       0   536.4      .1       0     600     .12       0
     630      .1       0     720     .06       0     850      .1       0
Bank Sta=514.4,536.4
XS Rating Curve= 0 ,0
Exp/Cntr=0.3,0.1

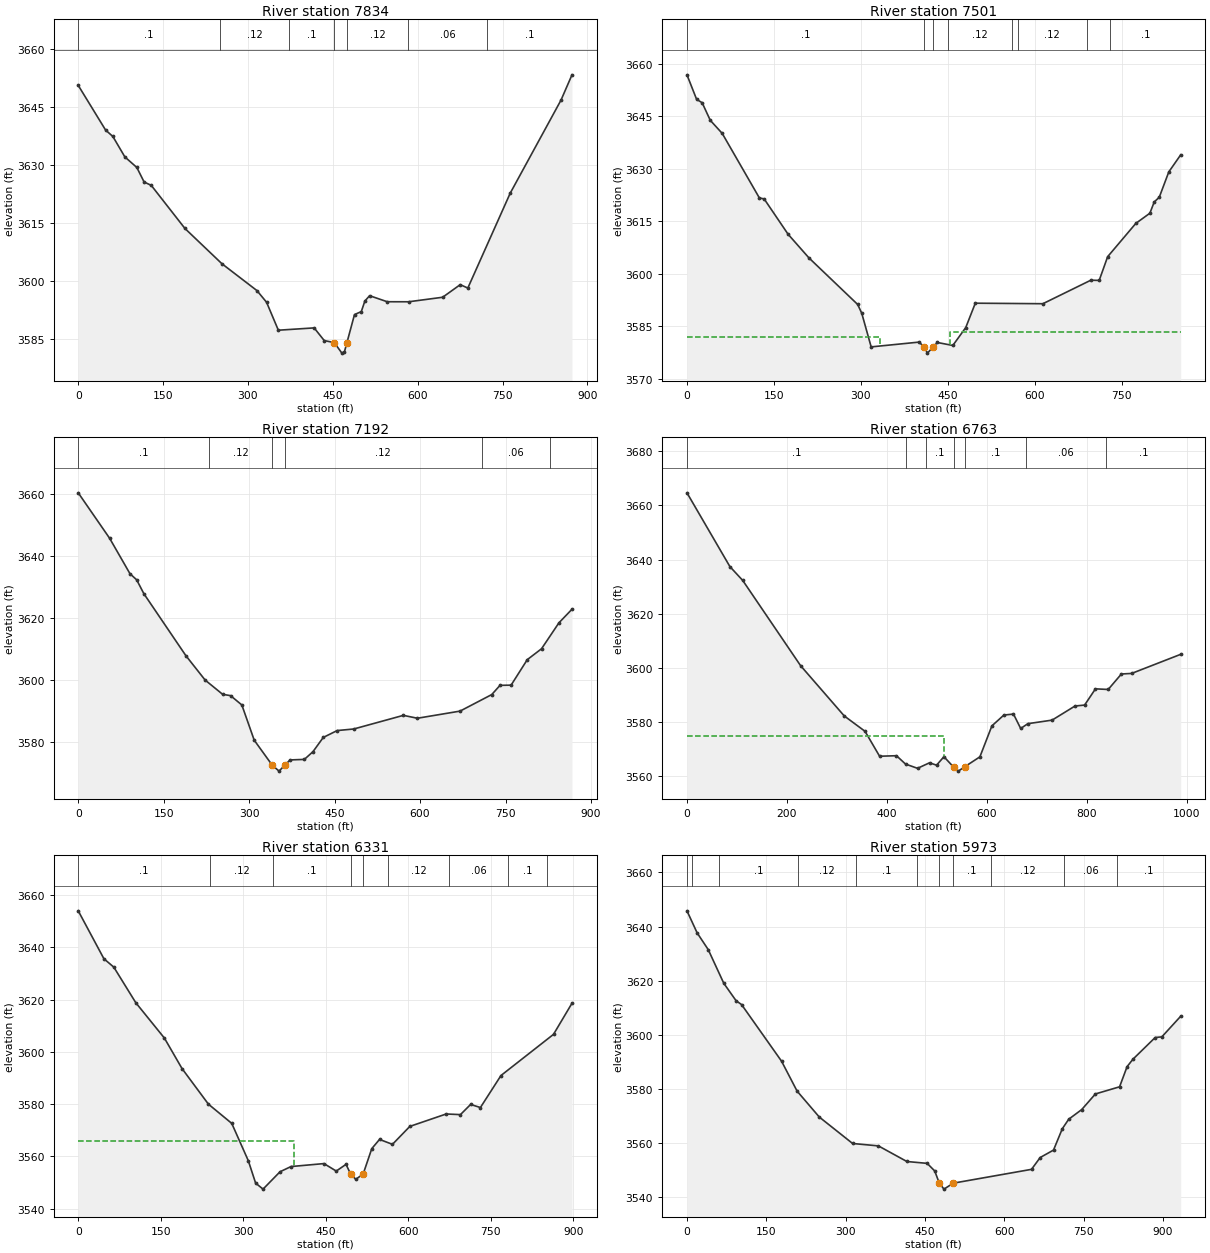
Type RM Length L Ch R = 1 ,7834    ,331.1,333.6,331.3
XS GIS Cut Line= 3
2295899.06411337619546.8174248812295784.09342488619223.866685728
2295551.47031703618747.737648858
#Sta/Elev= 30
       0 3650.57    48.4    3639    61.2 3637.35    82.4 3632.06   103.6 3629.32
   116.4 3625.57   129.1 3624.69   188.6 3613.54     254 3604.41   315.9 3597.46
   332.9 3594.44   353.7 3587.21     417 3587.81   434.8 3584.53   452.6    3584
     466 3581.28   470.4 3581.57  474.85 3583.96   488.3 3591.26   500.3 3592.02
   506.6 3594.75     515 3596.14   546.1 3594.58     584 3594.57   644.1 3595.74
   675.2    3599   688.6 3598.12   763.5 3622.67   853.3 3646.76   872.7  3653.3
#Mann= 7 ,-1,0
       0      .1       0     250     .12       0  372.81      .1       0
   452.6    .045       0  474.85     .12       0  582.81     .06       0
  722.81      .1       0
Bank Sta=452.6,474.85
XS Rating Curve= 0 ,0
Exp/Cntr=0.3,0.1

Type RM Length L Ch R = 1 ,7501    ,302.5,308.2,300.4
XS GIS Cut Line= 2
2296226.98166091619378.8647767752295744.48991288 618677.35430267
#Sta/Elev= 30
       0 3656.88    16.6 3649.89    26.2  3648.9    40.2 3643.88    60.8 3640.14
   124.9 3621.69   133.1 3621.42   174.4 3611.32   210.3 3604.57   294.4 3591.25
   301.4 3588.74   317.6 3579.13   400.1  3580.5   408.8 3579.17   414.7 3577.35
  424.993579.244   431.8 3580.39   458.4 3579.54   480.7 3584.65   497.2 3591.62
   613.7 3591.47   696.4 3598.19   710.8 3598.13   725.4 3604.91     774 3614.43
   798.2 3617.33   805.7 3620.55   814.4  3621.9   830.8 3629.13   851.4 3634.03
#Mann= 8 ,-1,0
       0      .1       0   408.8    .045       0  424.99      .1       0
     450     .12       0     560      .1       0     570     .12       0
     690     .06       0     730      .1       0
#XS Ineff= 2 , 0
          332.18 3581.93  454.31         3583.51
Permanent Ineff=
       F       F
Bank Sta=408.8,424.99
XS Rating Curve= 0 ,0
Exp/Cntr(USF)=0,0
Exp/Cntr=0.3,0.1

Type RM Length L Ch R = 1 ,7192    ,432.8,429.5,424.3
XS GIS Cut Line= 3
2296420.35627188 619305.023965892296266.77741936619037.630614748
2295951.22700276618576.989345623
#Sta/Elev= 30
       0 3660.44    55.2 3645.76    90.8 3634.37   102.6 3632.39   115.1 3627.95
   188.9 3607.95   222.7 3600.08   253.5 3595.47   267.4 3595.05   287.2 3592.04
   308.9 3580.69  340.393572.661   352.5 3570.71   362.5 3572.62   371.9 3574.32
   396.9 3574.49   412.1 3576.99   430.1 3581.57   454.5 3583.79   483.5 3584.29
   570.7 3588.69   595.4 3587.76   670.2 3590.06   725.9  3595.4   740.4 3598.37
   759.8 3598.43   788.2 3606.65   813.2 3610.16   843.8 3618.53   866.7 3622.91
#Mann= 6 ,-1,0
       0      .1       0     230     .12       0  340.39    .045       0
   362.5     .12       0  708.36     .06       0  828.36      .1       0
Bank Sta=340.39,362.5
XS Rating Curve= 0 ,0
Exp/Cntr=0.3,0.1

Type RM Length L Ch R = 1 ,6763    ,421.9,432.1,432.3
XS GIS Cut Line= 3
2296747.51423226619135.7641529972296640.66414748618761.984725357
     2296141.308      618430.962
#Sta/Elev= 30
       0 3664.67    85.9 3637.39   111.6 3632.26   227.3 3600.76   314.7 3582.16
   356.3 3576.47   385.4 3567.26   419.2 3567.45   437.3 3564.36   461.3 3562.79
   485.3 3564.83   499.4 3563.95   514.1 3567.08   533.3 3563.28   542.9 3561.75
555.56353563.341   586.1 3567.04   610.1 3578.49   634.1 3582.49   653.3 3582.85
   667.7 3577.52   682.1  3579.3   730.5 3580.61   776.4 3585.83   795.6 3586.18
   817.3 3592.18   842.8 3591.95   869.2 3597.67   889.7 3597.88   987.9 3604.95
#Mann= 7 ,-1,0
       0      .1       0  438.75     .12       0  478.75      .1       0
   533.3    .045       0555.5635      .1       0  678.75     .06       0
  838.75      .1       0
#XS Ineff= 2 , 0
          514.08 3574.69
Permanent Ineff=
       F       F
Bank Sta=533.3,555.5635
XS Rating Curve= 0 ,0
Exp/Cntr=0.3,0.1

Type RM Length L Ch R = 1 ,6331    ,355.5,357.5,341
XS GIS Cut Line= 4
2296933.94538652619049.8324644362296935.75700768618786.256338936
 2296732.3173059618365.0120484512296687.81985192618204.806145611
#Sta/Elev= 30
       0 3653.99    46.7 3635.65    64.7 3632.44   104.7 3618.82   156.7 3605.29
   188.7 3593.64   236.7 3580.02   279.1 3572.67   309.2 3558.39   322.5 3549.83
     336 3547.51   366.9 3554.16   386.9 3556.15   446.8 3557.28   469.1 3554.42
   486.9 3556.99  495.213553.281   504.6 3551.26     518 3553.28   533.7    3563
   547.8 3566.53   571.3 3564.65   602.9 3571.51     669 3576.26   694.9 3576.02
   713.4 3579.91   731.2 3578.73   768.6 3590.98   864.1 3606.73   897.7 3618.63
#Mann= 9 ,-1,0
       0      .1       0     240     .12       0  353.58      .1       0
  495.21    .045       0     518      .1       0  563.58     .12       0
  673.58     .06       0  781.38      .1       0  851.38     .12       0
#XS Ineff= 2 , 0
          392.78 3566.07
Permanent Ineff=
       F       F
Bank Sta=495.21,518
XS Rating Curve= 0 ,0
Exp/Cntr=0.3,0.1

Type RM Length L Ch R = 1 ,5973    ,192.9,202,210.7
XS GIS Cut Line= 4
2297077.62631629619011.4921484832297185.85651049618673.638434163
2296947.45756922618419.1512207792296900.65532308618193.915411232
#Sta/Elev= 30
       0 3645.81    19.2 3637.67    40.2 3631.48    69.6 3619.04    92.9 3612.58
   103.2 3611.18   178.8 3590.26   208.2  3579.2   250.2 3569.61   313.2 3559.84
   361.9 3558.96   415.7 3553.19   454.1  3552.5   468.4  3549.7  476.943545.242
   485.9 3542.98   503.4 3545.18   651.4 3550.29   667.8 3554.66     693 3557.41
   709.6 3565.29   721.8 3568.82   746.3 3572.37   772.2 3578.15   817.9 3580.79
   832.1 3588.24   843.2 3590.99   885.2    3599   897.8 3599.24   933.5 3606.87
#Mann= 11 ,-1,0
       0      .1       0      10     .12       0      60      .1       0
     210     .12       0     320      .1       0  434.77     .12       0
  476.94    .045       0   503.4      .1       0  574.77     .12       0
  713.47     .06       0  813.47      .1       0
Bank Sta=476.94,503.4
XS Rating Curve= 0 ,0
Exp/Cntr(USF)=0,0
Exp/Cntr=0.3,0.1

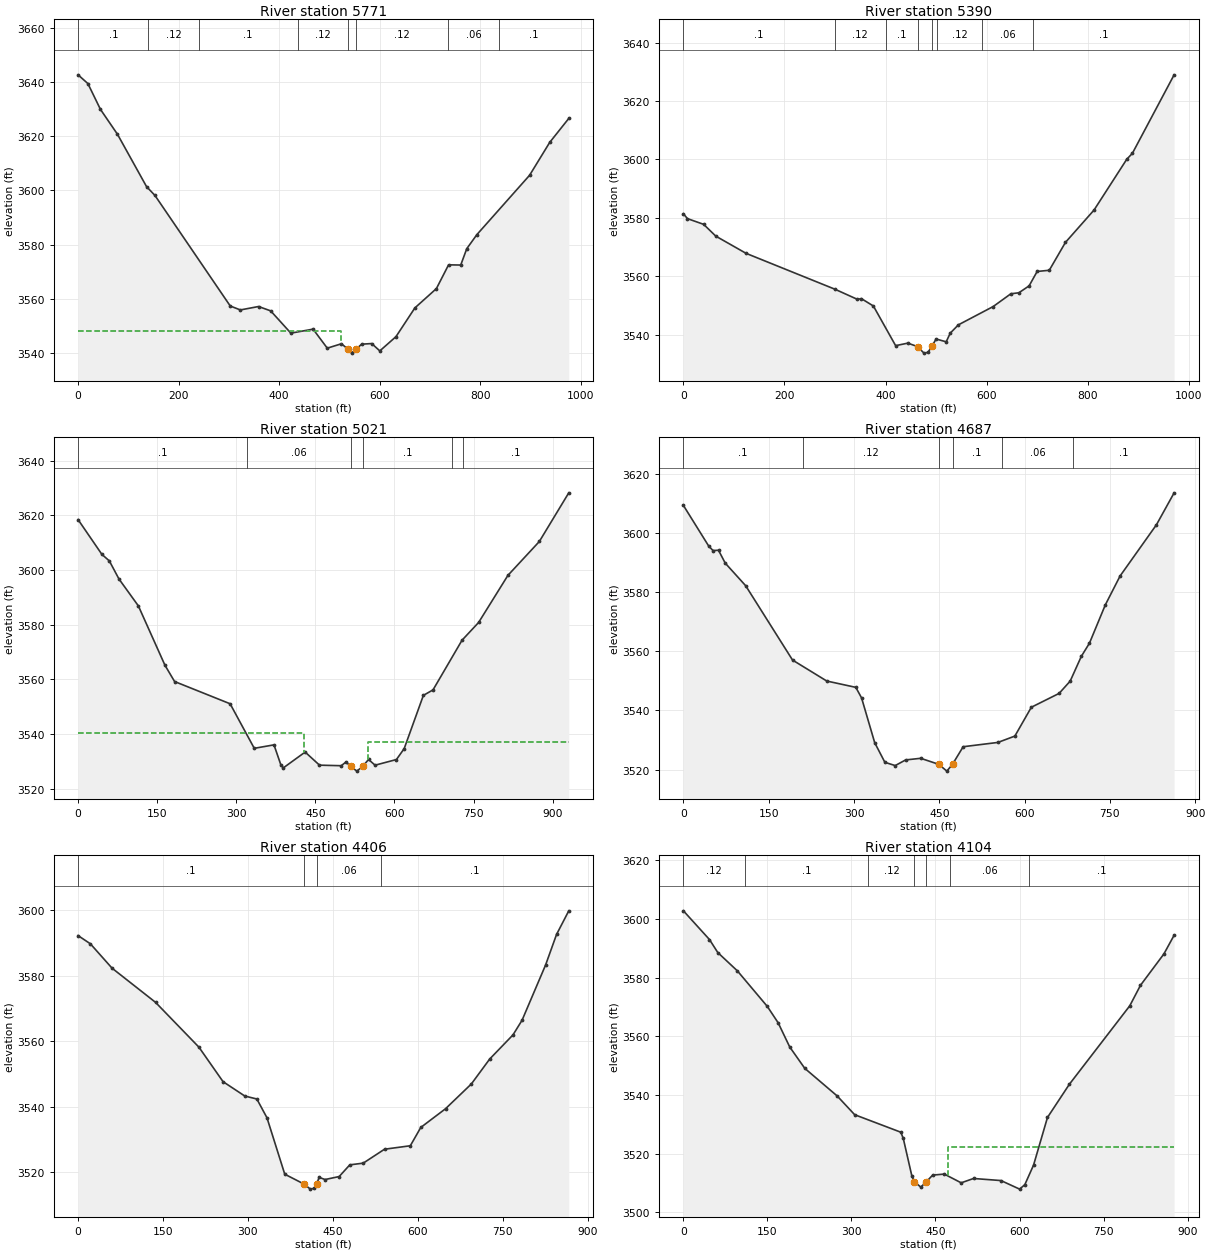
Type RM Length L Ch R = 1 ,5771    ,378.8,381.3,375.8
XS GIS Cut Line= 4
2297157.69366541619035.8471502382297241.22600276618751.348102331
 2297281.4211277618353.4418944092297247.83280185 618075.79549862
#Sta/Elev= 30
       0 3642.63    19.5 3639.41    44.5  3629.9    78.3 3620.74   136.2 3601.42
   152.9 3598.18   302.7 3557.42   322.8 3555.97     359 3557.23   383.1 3555.63
   423.3 3547.41   467.5 3548.89   495.7 3541.88   523.9  3543.5  536.273541.614
   543.9 3540.05  553.713541.626   564.1 3543.35   584.1 3543.58   600.2 3540.87
   632.4 3546.13     670 3556.72   712.8 3563.84     737 3572.59   761.2 3572.52
   773.2 3578.55   793.4 3583.75   898.2 3605.62   938.2 3617.73   976.1 3626.56
#Mann= 8 ,-1,0
       0      .1       0     140     .12       0     240      .1       0
  436.51     .12       0  536.27    .045       0  553.71     .12       0
  736.44     .06       0  836.44      .1       0
#XS Ineff= 2 , 0
          523.74 3548.37
Permanent Ineff=
       F       F
Bank Sta=536.27,553.71
XS Rating Curve= 0 ,0
Exp/Cntr=0.3,0.1

Type RM Length L Ch R = 1 ,5390    ,371.1,368.6,354.6
XS GIS Cut Line= 4
 2297556.3375069619009.2043059942297560.48916127618608.040611989
2297554.27372865618213.0030556842297506.63773364618044.680073739
#Sta/Elev= 30
       0 3581.39       8 3579.73      40 3577.78      64 3573.75     124 3567.85
     300 3555.56   344.3  3552.1   352.2 3552.35     376 3549.82     420 3536.25
   444.1 3537.11   463.4 3535.93   476.1 3533.69   484.1 3533.96  491.633536.018
   500.1 3538.52   520.1 3537.57   528.1 3540.53   544.1 3543.36   613.1 3549.64
   648.1 3554.01   663.9 3554.35   684.2 3556.72   700.1 3561.65   724.1 3562.05
   756.1  3571.6   812.7 3582.67   877.4 3600.04   888.6 3602.09   971.2 3628.96
#Mann= 8 ,-1,0
       0      .1       0     300     .12       0     400      .1       0
   463.4    .045       0  491.63      .1       0  501.19     .12       0
  591.19     .06       0  691.19      .1       0
Bank Sta=463.4,491.63
XS Rating Curve= 0 ,0
Exp/Cntr=0.3,0.1

Type RM Length L Ch R = 1 ,5021    ,332,334.5,330.1
XS GIS Cut Line= 2
2298037.78458769618840.9652916962297584.36776552618028.426296217
#Sta/Elev= 30
       0 3618.42    45.1 3605.73    59.3 3603.32    77.5 3596.73   114.3 3586.89
   164.7 3565.21     183 3559.24   288.3 3551.11   334.1 3534.83   371.5 3536.09
   384.5  3528.8   389.1 3527.66   430.6 3533.46   457.8 3528.67     499 3528.47
   508.2 3529.85  516.713528.217   528.7 3526.49  539.563528.187   550.8 3530.75
   563.2 3528.66   603.7 3530.73   618.4 3534.72   654.8 3554.18   673.1 3556.19
   728.1 3574.34   759.6 3580.84   815.1 3598.04   874.7 3610.43   930.5 3628.21
#Mann= 6 ,-1,0
       0      .1       0     320     .06       0  516.71    .045       0
  539.56      .1       0     710     .06       0     730      .1       0
#XS Ineff= 2 , 0
          428.16 3540.48  549.46         3537.17
Permanent Ineff=
       F       F
Bank Sta=516.71,539.56
XS Rating Curve= 0 ,0
Exp/Cntr(USF)=0,0
Exp/Cntr=0.3,0.1

Type RM Length L Ch R = 1 ,4687    ,281.7,280.6,280.3
XS GIS Cut Line= 3
2298286.31203411618688.7673880122297959.78688663618190.231008278
2297806.92177326617971.275532731
#Sta/Elev= 30
       0 3609.38    44.6 3595.59    52.1 3594.11    61.7 3594.22    73.5 3589.87
   109.5 3582.21   191.9 3557.06   252.1 3549.96   303.2 3547.82   313.3 3544.25
   336.4  3529.1   354.3 3522.45   372.5 3521.35   390.8 3523.26   417.3 3523.81
   449.1 3521.77   463.3 3519.47   473.43521.837     492 3527.73   553.1 3529.18
   582.9 3531.33   611.9 3541.09   660.7 3545.77   680.2 3549.93   699.8 3558.31
   714.1 3562.77     742 3575.73     768 3585.52     832 3602.87     863 3613.65
#Mann= 6 ,-1,0
       0      .1       0     210     .12       0   449.1    .045       0
   473.4      .1       0     560     .06       0  685.95      .1       0
Bank Sta=449.1,473.4
XS Rating Curve= 0 ,0
Exp/Cntr=0.3,0.1

Type RM Length L Ch R = 1 ,4406    ,303.2,302.6,300
XS GIS Cut Line= 3
2298440.44339905618585.4936092292298324.19669676618270.419954852
2297985.29638525617861.656342864
#Sta/Elev= 30
       0 3592.21    21.7 3589.71      60 3582.27   136.8 3571.84   213.5 3558.15
   256.1 3547.62   294.5 3543.24   315.8 3542.33   333.7 3536.59   365.1 3519.38
   399.8 3516.31   410.2 3514.82   417.3 3515.07  421.583516.432   425.8 3518.41
   436.3 3517.75   461.2 3518.66     480 3522.23   503.7 3522.75   541.3    3527
   586.9 3528.06   605.4 3533.65   649.1 3539.36   694.7 3546.92   727.1 3554.53
   768.3 3561.91   784.3 3566.38   825.9 3583.26   845.2 3592.56   866.8 3599.77
#Mann= 4 ,-1,0
       0      .1       0   399.8    .045       0  421.58     .06       0
  535.83      .1       0
Bank Sta=399.8,421.58
XS Rating Curve= 0 ,0
Exp/Cntr=0.3,0.1

Type RM Length L Ch R = 1 ,4104    ,535.7,542.7,546.2
XS GIS Cut Line= 3
2298727.94116657618415.6362372732298575.46471309618104.664522954
2298170.19834992617763.598771765
#Sta/Elev= 30
       0 3602.83    46.5 3593.04    61.4 3588.59    96.3 3582.36   149.8 3570.22
   169.1 3564.65   189.8 3556.39   216.6 3549.12   274.5 3539.69   305.7  3533.3
   388.1 3527.33   392.5  3525.2   407.9 3512.33   412.53510.376   423.8 3508.62
   433.5  3510.4   444.9  3512.7   465.7 3513.05   495.9 3510.07   517.9 3511.55
   566.9 3510.84   600.2 3507.92   609.5 3509.45   625.1 3516.13   649.9 3532.36
     689 3543.68   796.9 3570.46   815.9 3577.42   857.8 3588.14     876 3594.51
#Mann= 7 ,-1,0
       0     .12       0     110      .1       0     330     .12       0
   412.5    .045       0   433.5     .12       0  476.34     .06       0
  616.34      .1       0
#XS Ineff= 2 , 0
                          472.92         3522.14
Permanent Ineff=
       F       F
Bank Sta=412.5,433.5
XS Rating Curve= 0 ,0
Exp/Cntr(USF)=0,0
Exp/Cntr=0.3,0.1

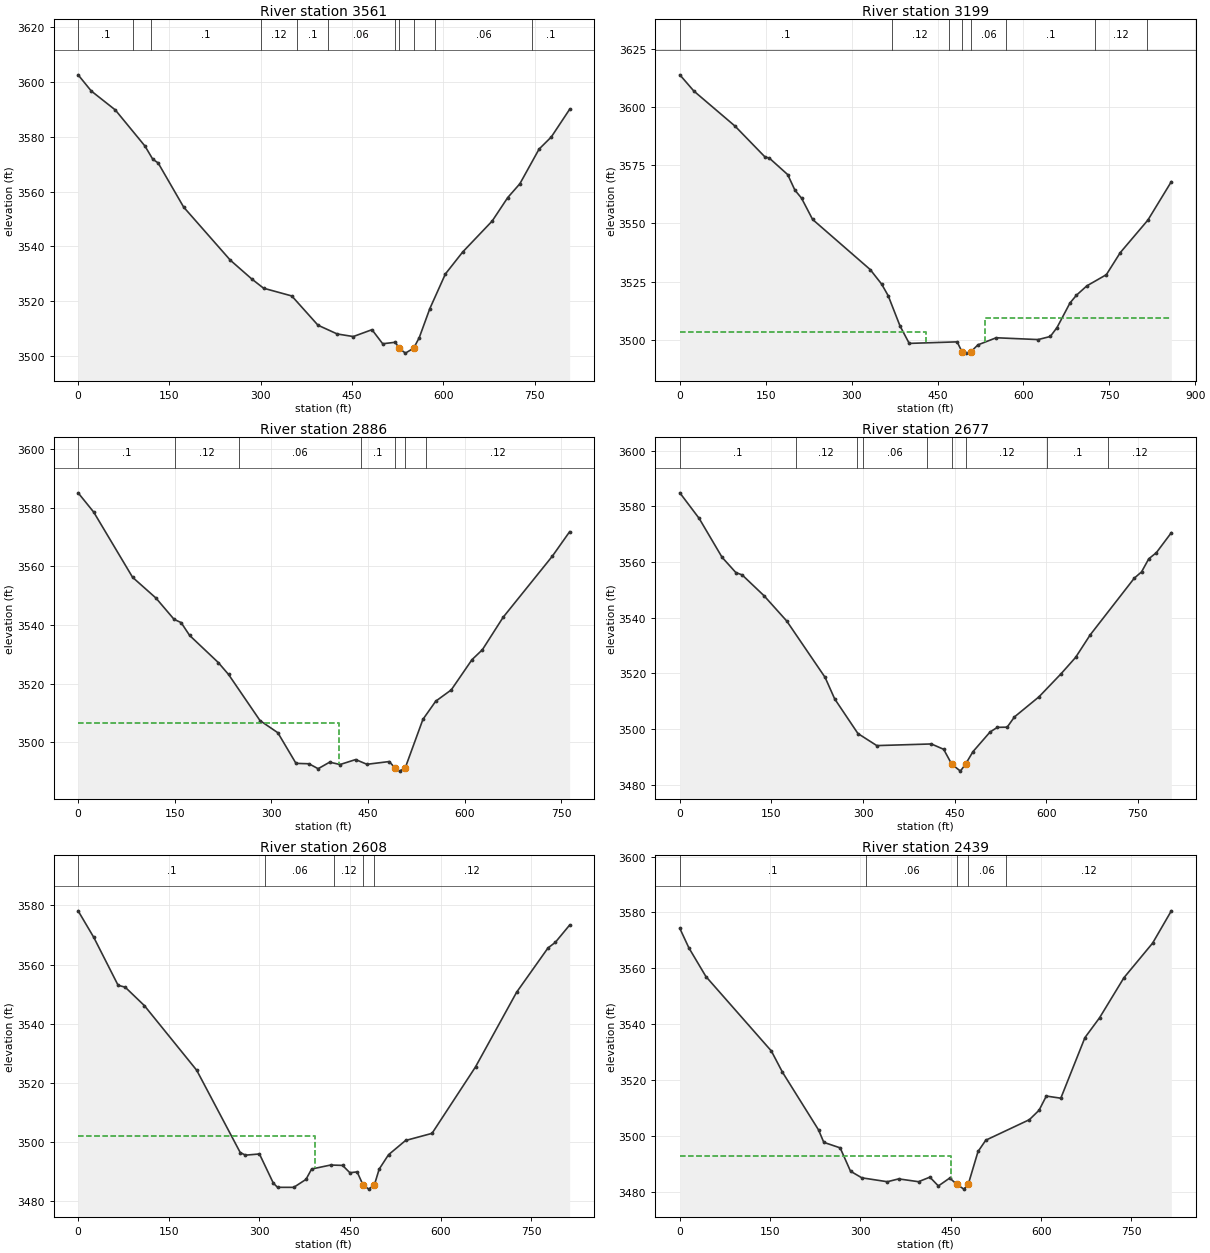
Type RM Length L Ch R = 1 ,3561    ,357.8,361.8,367.3
XS GIS Cut Line= 3
2298913.77834562618296.8644221222298680.40806822617781.197580638
2298528.58022398617593.839529971
#Sta/Elev= 30
       0 3602.61    21.6 3596.71    61.1 3589.79   109.8 3576.62   122.6 3571.82
   131.4 3570.47   173.3 3554.36   249.9    3535   285.2 3528.13   304.6 3524.76
   350.9 3521.94   393.9 3511.27   425.5 3508.07   451.9 3507.13   482.6 3509.63
   500.2  3504.5   520.9 3505.04  527.343502.844   537.5 3501.08   551.1  3502.9
   560.2 3506.71   577.6 3517.31   603.2 3529.97   631.6 3537.98     680 3549.27
   705.5 3557.81   725.5 3562.88     757 3575.51   777.1 3579.94   807.2 3590.03
#Mann= 11 ,-1,0
       0      .1       0      90     .12       0     120      .1       0
     300     .12       0     360      .1       0     410     .06       0
     520     .12       0  527.34    .045       0   551.1     .12       0
  586.02     .06       0  746.02      .1       0
Bank Sta=527.34,551.1
XS Rating Curve= 0 ,0
Exp/Cntr=0.3,0.1

Type RM Length L Ch R = 1 ,3199    ,312.8,313.4,313
XS GIS Cut Line= 3
 2299062.7965999618289.5386314742299044.12448377617684.371716251
2298877.27241279617494.226240704
#Sta/Elev= 30
       0 3613.77    24.4 3606.83    96.4 3591.75   148.4 3578.58   156.4 3577.98
   188.4 3570.92   200.9 3564.28   212.5 3560.82   231.9 3551.66   332.5 3530.14
   352.5 3523.88   363.9 3518.91   384.5 3505.95   400.6 3498.44   484.3  3499.1
   492.6 3494.92   500.6 3494.26   508.6 3494.93   520.6 3497.81   552.6 3500.86
   625.7 3500.08     647 3501.41   658.7 3505.23   681.4 3515.81   692.7 3519.14
   710.8 3523.14   744.9 3527.95   769.2 3537.42   817.4 3551.38   858.4  3567.9
#Mann= 8 ,-1,0
       0      .1       0     370     .12       0     470     .06       0
   492.6    .045       0   508.6     .06       0     570      .1       0
  725.45     .12       0  815.45      .1       0
#XS Ineff= 2 , 0
           429.5 3503.53  532.13         3509.21
Permanent Ineff=
       F       F
Bank Sta=492.6,508.6
XS Rating Curve= 0 ,0
Exp/Cntr=0.3,0.1

Type RM Length L Ch R = 1 ,2886    ,208.2,208.6,204.9
BEGIN DESCRIPTION:
Structure XS 4
END DESCRIPTION:
XS GIS Cut Line= 4
2299258.96910897618165.2100656092299313.15279608617698.525380958
2299311.89268711617628.4124514582299336.69290224617406.495599078
#Sta/Elev= 30
       0 3585.08    24.2 3578.51    84.6 3556.27   120.8 3549.21     149 3541.94
   159.9 3540.84   173.2 3536.44   217.6 3527.22   233.6 3523.14   282.5 3507.41
   310.1 3503.28   338.3 3492.83   358.4 3492.69   372.7 3491.01   390.6 3493.24
   406.7 3492.43   430.9 3494.12   448.5 3492.51   483.2 3493.45   491.8 3491.29
   499.2 3490.18  507.94 3491.29   535.4 3507.83   555.3 3514.03   579.4 3517.88
   611.6 3528.19   627.7 3531.57   659.9 3542.63   736.4 3563.49   763.2 3571.82
#Mann= 7 ,-1,0
       0      .1       0     150     .12       0     250     .06       0
     440      .1       0   491.8    .045       0  507.94      .1       0
  539.82     .12       0
#XS Ineff= 2 , 0
          404.33 3506.69
Permanent Ineff=
       F       F
Bank Sta=491.8,507.94
XS Rating Curve= 0 ,0
Exp/Cntr=0.3,0.1

Type RM Length L Ch R = 1 ,2677    ,67.9,68.7,66.5
BEGIN DESCRIPTION:
Structure XS 3
END DESCRIPTION:
XS GIS Cut Line= 5
2299317.11018278618180.6579848572299474.89321809617907.751214639
 2299448.4525973 617854.599126722299454.21058969617697.391890652
2299442.17297494617424.539289701
#Sta/Elev= 30
       0 3584.82    31.7 3575.61    69.2 3561.66    91.8 3556.17     102 3555.35
     138 3547.84     175  3538.8   237.9 3518.53   253.6 3510.81   291.7 3498.36
   322.6 3494.03     412 3494.62   432.1  3492.7   445.2  3487.4   459.5 3484.86
   468.1 3487.44   480.2 3491.88   508.1 3498.92   520.1 3500.59   536.1 3500.65
   548.1 3504.34   588.2 3511.55   624.2 3519.79   648.2 3525.71   672.1  3533.8
   744.3 3554.17   756.2 3556.42     768 3561.12   780.4 3563.31     805 3570.51
#Mann= 9 ,-1,0
       0      .1       0     190     .12       0     290      .1       0
     300     .06       0   404.6     .12       0   445.2    .045       0
   468.1     .12       0  601.91      .1       0  701.91     .12       0
Bank Sta=445.2,468.1
XS Rating Curve= 0 ,0
Exp/Cntr(USF)=0,0
Exp/Cntr=0.3,0.1

Type RM Length L Ch R = 1 ,2608    ,163,169,173.7
BEGIN DESCRIPTION:
Structure XS 2
END DESCRIPTION:
XS GIS Cut Line= 4
2299375.32408771 618176.364568932299565.45821265617889.700811325
2299517.19339632617809.2594507732299514.26825593617433.378911464
#Sta/Elev= 30
       0 3578.13      26 3569.14    66.2 3552.99    77.9 3552.36   109.7 3546.13
   196.3 3524.31   268.4 3496.52   277.1 3495.64   300.2 3496.04   323.2 3486.19
   330.2 3484.78     357 3484.77   377.2 3487.45   386.6 3490.96   418.2 3492.31
   437.8 3492.18   449.9 3489.71   461.9 3489.99  471.633485.615   481.2 3484.17
   490.5 3485.62   498.4 3490.93   513.9 3495.79   542.1 3500.59   585.9    3503
   657.9 3525.44   725.9 3550.63   777.9  3565.6   789.9 3567.46   813.7 3573.32
#Mann= 5 ,-1,0
       0      .1       0     310     .06       0  423.99     .12       0
  471.63    .045       0   490.5     .12       0
#XS Ineff= 2 , 0
          392.06 3502.07
Permanent Ineff=
       F       F
Bank Sta=471.63,490.5
XS Rating Curve= 0 ,0
Exp/Cntr(USF)=0,0
Exp/Cntr=0.3,0.1

Type RM Length L Ch R = 1 ,2439    ,42.8,42.6,42.6
BEGIN DESCRIPTION:
Structure XS 1
END DESCRIPTION:
XS GIS Cut Line= 3
2299431.72218367618186.0014990642299696.51292021617759.537296209
2299670.14173467 617446.21951825
#Sta/Elev= 30
       0 3574.29    15.1 3567.29    43.3 3557.06     152 3530.38   170.5 3522.77
   230.4 3502.11   239.1 3497.66   266.3 3495.68   283.5 3487.32   302.3 3484.95
   344.7 3483.55   363.5 3484.57   396.5 3483.56   415.3 3485.19   429.4 3482.04
   448.3 3484.87   459.9 3482.64   471.8  3480.9  479.04 3482.61   495.3 3494.38
   508.2 3498.43   580.6 3505.78   596.7 3509.16   608.7 3514.24   632.8 3513.47
   672.9 3535.19   697.1 3542.26   737.7 3556.64   785.3 3569.03   816.4 3580.59
#Mann= 5 ,-1,0
       0      .1       0     310     .06       0   459.9    .045       0
  479.04     .06       0  541.98     .12       0
#XS Ineff= 2 , 0
          450.54 3492.62
Permanent Ineff=
       F       F
Bank Sta=459.9,479.04
XS Rating Curve= 0 ,0
Exp/Cntr=0.3,0.1