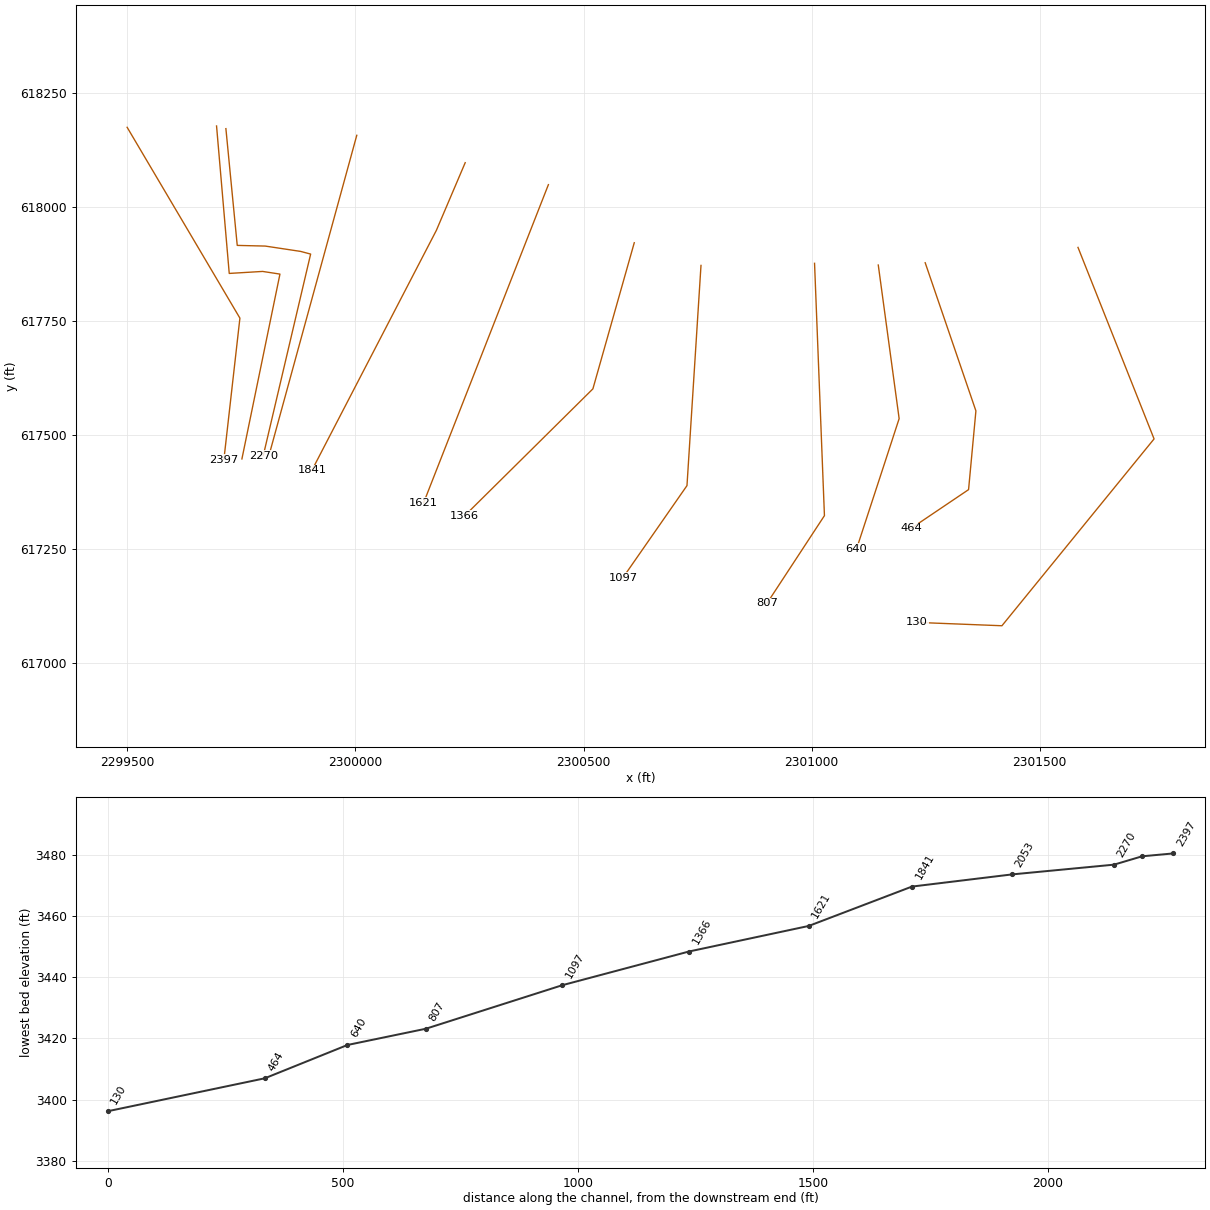
HEC-RAS study YOKUMRN.prj: YOKUMRN

--- YOKUMRN.g01 (geometry) --- (continued)

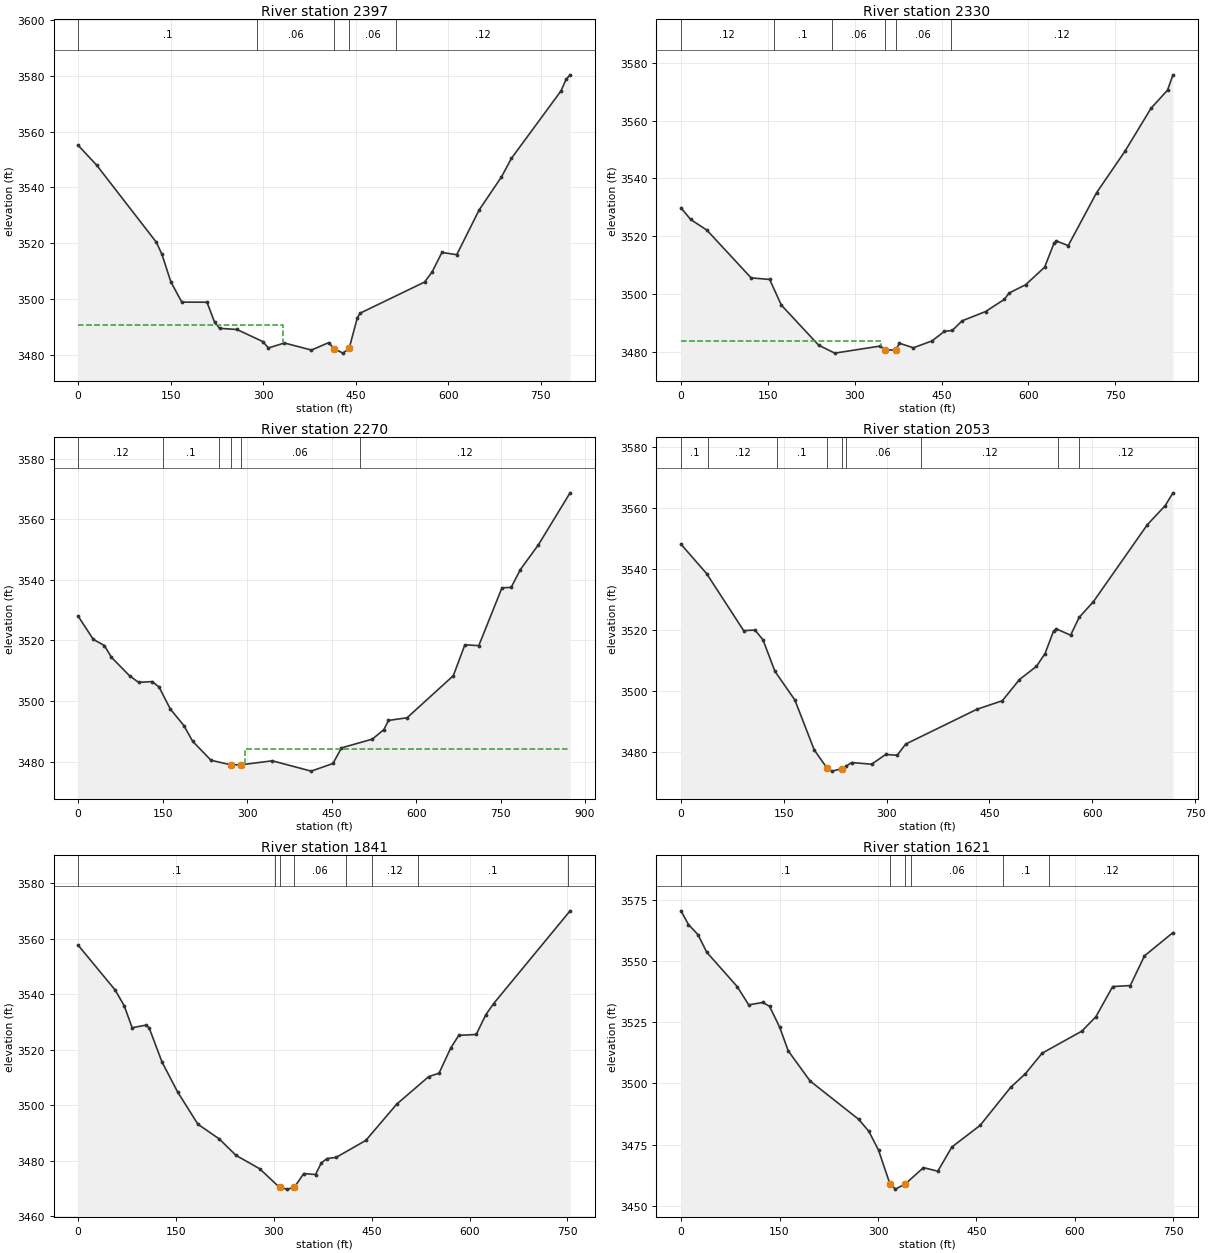
Type RM Length L Ch R = 1 ,2397    ,57.9,66.8,78.3
XS GIS Cut Line= 3
2299499.64255401618174.9019987382299746.81691644617756.606923866
2299711.71523183617446.542043191
#Sta/Elev= 30
       0 3555.06    29.9 3547.97   126.9 3520.27     136 3515.91   150.4 3506.06
   168.1 3498.83     209 3498.78   221.2 3491.67   229.4 3489.41   257.5    3489
   299.4 3484.68   308.6 3482.38   334.6 3484.15   378.4 3481.63   406.2 3484.26
   415.5 3482.11   429.4 3480.52   439.53482.184   452.7 3493.09   457.2 3494.83
   561.8    3506   573.9 3509.55     590 3516.62   614.1 3515.83   650.3 3531.84
   686.6 3543.72   702.7 3550.36   783.2 3574.58   791.2 3578.66   797.9 3580.33
#Mann= 5 ,-1,0
       0      .1       0     290     .06       0   415.5    .045       0
   439.5     .06       0  515.87     .12       0
#XS Ineff= 2 , 0
          332.09 3490.67
Permanent Ineff=
       F       F
Bank Sta=415.5,439.5
XS Rating Curve= 0 ,0
Exp/Cntr(USF)=0,0
Exp/Cntr=0.3,0.1

Type RM Length L Ch R = 1 ,2330    ,60,59.6,58.4
XS GIS Cut Line= 5
2299695.62695972618177.8271391222299723.41579337 617854.59912672
2299796.54430296617858.9868372962299834.57112795617853.136556529
2299751.20462701617448.004613383
#Sta/Elev= 30
       0 3529.84    16.7 3525.81    44.8 3522.11   121.1 3505.61   153.2 3505.06
   173.3 3496.19   237.7 3482.33   265.6 3479.57   343.8 3482.01   353.2 3480.65
  370.553480.626   377.3 3482.99   401.4 3481.42   433.7 3483.81   455.1 3487.11
   468.6 3487.41   485.6 3490.75   526.2 3493.97   558.6 3498.19   566.8 3500.37
   595.4 3503.25   628.1  3509.3   644.4 3517.64   648.5 3518.37   668.9 3516.78
   717.9 3535.09   766.9 3549.43   811.8 3564.25   840.4 3570.55   849.8 3575.86
#Mann= 6 ,-1,0
       0     .12       0     160      .1       0     260     .06       0
   353.2    .045       0  370.55     .06       0  466.15     .12       0
#XS Ineff= 2 , 0
          345.42 3483.75
Permanent Ineff=
       F       F
Bank Sta=353.2,370.55
XS Rating Curve= 0 ,0
Exp/Cntr(USF)=0,0
Exp/Cntr=0.3,0.1

Type RM Length L Ch R = 1 ,2270    ,234.7,217.4,203.1
XS GIS Cut Line= 6
2299716.10294241618171.9768583542299740.96663567617916.027074779
2299802.39458373617914.564504587 2299879.9108039617902.863943052
2299901.84935678617897.0136622842299798.00687315617455.317464342
#Sta/Elev= 30
       0 3528.05    26.9 3520.36    46.6 3518.34    59.1 3514.45    91.2 3508.36
   107.3 3506.17   131.4 3506.42   143.5 3504.67   163.8 3497.32   187.7  3491.9
   203.3  3486.7   235.9 3480.43  270.833478.926   288.4 3478.92   344.7 3480.25
   413.8 3476.84   452.4 3479.36   467.5 3484.52   522.3 3487.41   542.8 3490.57
     551 3493.59     584 3494.47   666.1 3508.38   686.6 3518.57   711.3  3518.3
   752.4  3537.4   768.8 3537.54   785.2 3543.45   816.9 3551.55   873.4 3568.78
#Mann= 6 ,-1,0
       0     .12       0     150      .1       0     250     .06       0
  270.83    .045       0   288.4     .06       0   499.7     .12       0
#XS Ineff= 2 , 0
                          296.02         3484.22
Permanent Ineff=
       F       F
Bank Sta=270.83,288.4
XS Rating Curve= 0 ,0
Exp/Cntr(USF)=0,0
Exp/Cntr=0.3,0.1

Type RM Length L Ch R = 1 ,2053    ,216.2,212.4,211.7
XS GIS Cut Line= 2
2300002.96974176618157.3331367852299813.17062285617465.166089748
#Sta/Elev= 30
       0 3548.13    37.5 3538.45    91.4 3519.76     108 3519.95   119.6 3516.75
     137 3506.42   166.1    3497   194.4 3480.59   213.4 3474.53   220.5 3473.64
   235.6  3474.5     240 3475.16     249 3476.46   278.1 3475.91   298.6 3479.11
   315.4 3478.86   327.8 3482.52   431.5 3493.92   468.8 3496.76   493.7  3503.7
   518.6 3508.04   531.1 3512.25   543.5 3519.61   547.7 3520.33   568.4 3518.26
   580.8  3524.1   601.6 3529.26   680.4 3554.56   706.4  3560.8   717.7    3565
#Mann= 9 ,-1,0
       0      .1       0      40     .12       0     140      .1       0
   213.4    .045       0   235.6      .1       0     240     .06       0
     350     .12       0     550      .1       0     580     .12       0
Bank Sta=213.4,235.6
XS Rating Curve= 0 ,0
Exp/Cntr(USF)=0,0
Exp/Cntr=0.3,0.1

Type RM Length L Ch R = 1 ,1841    ,218.7,219.6,220.1
XS GIS Cut Line= 3
2300240.63089704618097.3335727152300177.50424617617949.149197838
 2299904.5186589 617422.83377037
#Sta/Elev= 30
       0 3557.73    56.7 3541.56    70.6 3535.86    82.8 3527.93   104.5  3528.9
   108.9 3527.83   128.5 3515.59   152.3 3504.82   183.6 3493.09   216.1 3487.82
   242.1 3481.84   278.2 3477.03  308.85 3470.26   320.3 3469.67   331.2 3470.27
   345.8  3475.3   363.8 3474.94   372.8 3479.18   381.6 3480.72   395.4 3481.13
   440.9 3487.25   488.4 3500.38   537.5 3510.32   553.1  3511.5   571.1 3520.64
   583.4 3525.18   610.1 3525.49   624.9 3532.66   636.8 3536.65     754 3570.13
#Mann= 8 ,-1,0
       0      .1       0  301.07     .06       0  308.85    .045       0
   331.2     .06       0  411.07      .1       0  451.07     .12       0
  521.07      .1       0  751.07     .12       0
Bank Sta=308.85,331.2
XS Rating Curve= 0 ,0
Exp/Cntr=0.3,0.1

Type RM Length L Ch R = 1 ,1621    ,258.6,254.7,248.8
XS GIS Cut Line= 2
2300422.98485587618049.1824922792300149.44151451617351.752634535
#Sta/Elev= 30
       0 3570.48    11.4 3564.87    25.8 3560.76    39.2 3553.57    85.5 3539.56
   103.1 3532.07   124.6 3533.05   134.9 3531.46   150.4 3522.84   163.3 3513.27
   196.6 3500.97   270.7 3485.28   286.1 3480.39   300.8 3472.72     318 3459.07
   326.6 3456.79   341.7 3458.92   369.2 3465.57   391.1 3464.12   412.5 3473.99
   455.5 3482.82   502.1  3498.4   524.2 3503.86     550 3512.34   610.2 3521.29
   631.8  3527.2   657.4 3539.55   684.2 3539.95   705.8 3552.07   749.2 3561.59
#Mann= 6 ,-1,0
       0      .1       0     318    .045       0   341.7      .1       0
     350     .06       0     490      .1       0     560     .12       0
Bank Sta=318,341.7
XS Rating Curve= 0 ,0
Exp/Cntr=0.3,0.1

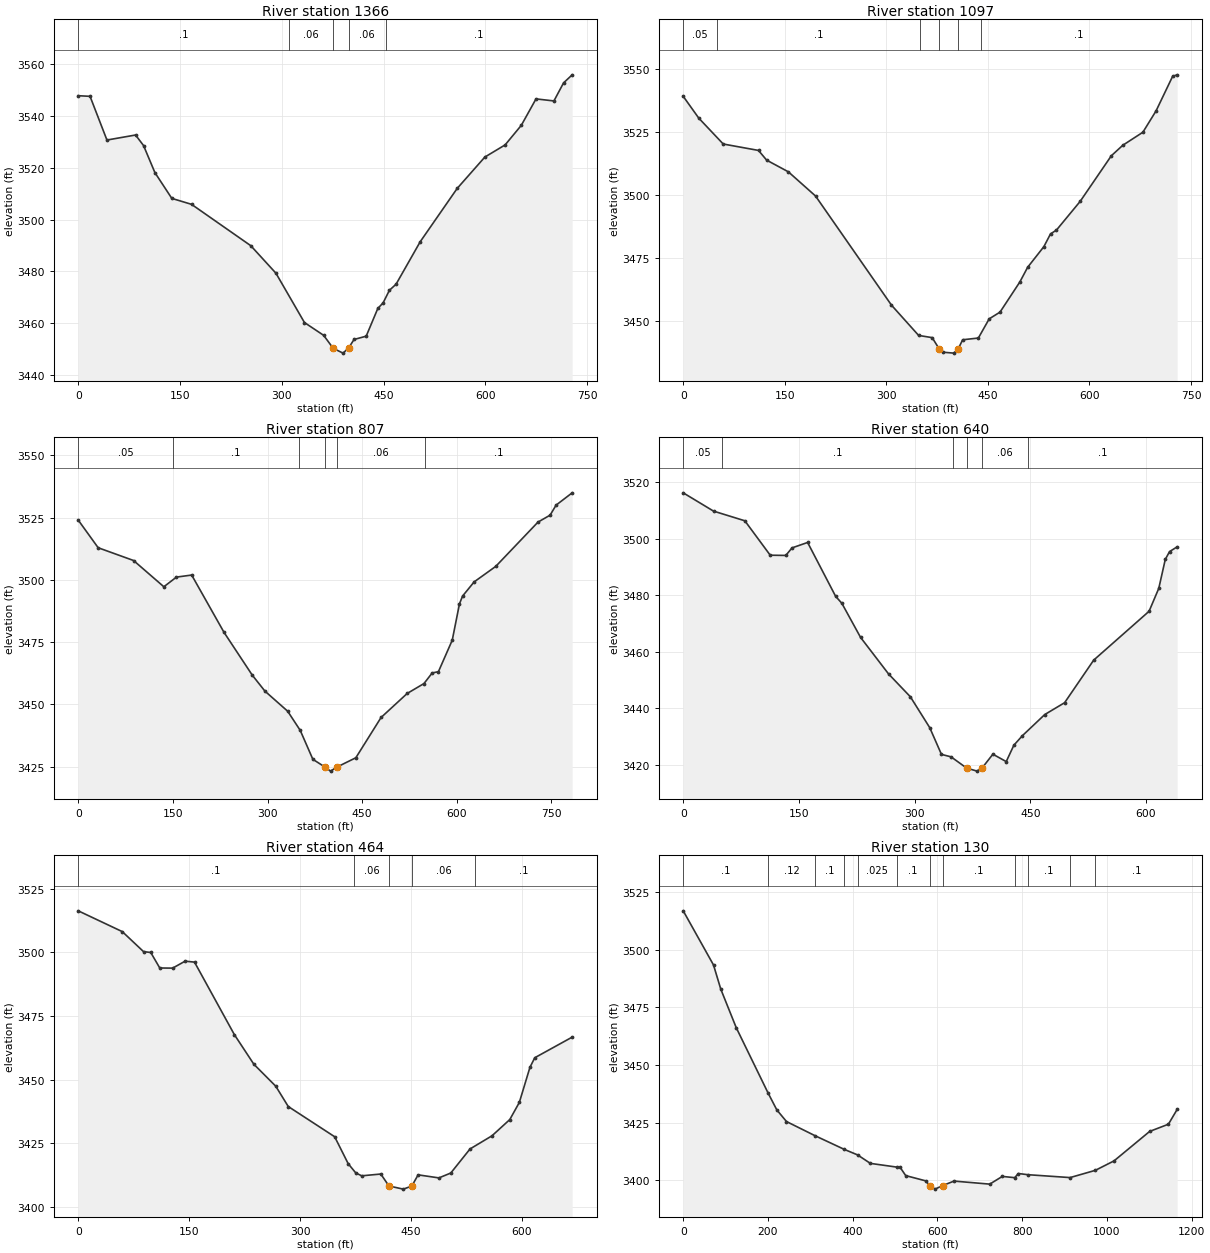
Type RM Length L Ch R = 1 ,1366    ,261.8,269.4,279.3
XS GIS Cut Line= 3
2300611.19589983617921.8773555462300520.51654793617601.574483528
 2300239.7030711617323.686147074
#Sta/Elev= 30
       0 3547.79    17.4 3547.55    42.3 3530.68    84.5 3532.62    96.3 3528.53
     113 3518.11   137.9 3508.16     167 3505.86   254.3  3489.9   291.4 3479.27
   333.4 3460.24   361.7  3455.3   375.8 3450.28   390.3 3448.43   398.5 3450.44
   406.5  3453.7   424.4 3454.97   441.5 3465.66   449.4 3467.86   458.6 3472.68
   468.4 3475.02   504.1 3491.46   558.5    3512   599.3 3524.11   629.2 3528.81
     653 3536.35   674.7 3546.56   701.1 3545.77   715.3 3552.74     728 3555.85
#Mann= 5 ,-1,0
       0      .1       0     310     .06       0   375.8    .045       0
   398.5     .06       0  452.89      .1       0
Bank Sta=375.8,398.5
XS Rating Curve= 0 ,0
Exp/Cntr(USF)=0,0
Exp/Cntr=0.3,0.1

Type RM Length L Ch R = 1 ,1097    ,289.3,290.2,291.5
XS GIS Cut Line= 3
2300757.45291901617872.1499690232300726.73894499617389.501805708
2300586.33220657617187.667119231
#Sta/Elev= 30
       0 3539.15      23  3530.5    59.1 3520.25   111.2 3517.71   123.2 3513.87
   155.3 3509.23   195.4 3499.66   307.6 3456.41   347.7 3444.42   367.7 3443.55
   378.5 3438.89   383.7 3437.77   399.7 3437.41  405.923438.959   412.7  3442.7
   435.9 3443.39   451.9 3450.99   467.9 3453.66   497.2 3465.61   508.7 3471.42
   532.7 3479.61   542.5 3484.66   551.2 3486.14   586.3 3497.54   632.3  3515.6
   649.2 3519.75   678.9 3524.92   698.4  3533.4   722.8 3547.06   729.5 3547.66
#Mann= 6 ,-1,0
       0     .05       0      50      .1       0     350     .06       0
   378.5    .045       0  405.92     .06       0     440      .1       0
Bank Sta=378.5,405.92
XS Rating Curve= 0 ,0
Exp/Cntr(USF)=0,0
Exp/Cntr=0.3,0.1

Type RM Length L Ch R = 1 ,807     ,169.7,166.9,162.2
XS GIS Cut Line= 3
2301006.35470192617876.8043413662301028.02840451617323.686147075
 2300902.2717693617131.852202855
#Sta/Elev= 30
       0    3524    31.6  3512.9    87.7 3507.77   135.7 3497.23   155.7 3501.11
   179.8 3501.93     231 3478.94   275.8 3461.74   295.9 3455.31   331.9 3447.25
   351.9 3439.52   371.9 3427.91  390.953424.832   399.9 3423.17   410.2 3424.82
     440 3428.54     480 3444.72   521.4 3454.37     548 3458.35     561  3462.6
   570.9 3463.12   592.8 3475.76   604.3 3490.41   609.2  3493.5   627.5 3499.18
   661.8 3505.42   728.7  3523.2   747.9 3525.99   757.4 3530.02   782.9 3534.96
#Mann= 6 ,-1,0
       0     .05       0     150      .1       0     350     .06       0
  390.95    .045       0   410.2     .06       0     550      .1       0
Bank Sta=390.95,410.2
XS Rating Curve= 0 ,0
Exp/Cntr=0.3,0.1

Type RM Length L Ch R = 1 ,640     ,173.3,175.9,179.1
XS GIS Cut Line= 4
2301146.04165203617872.9812855992301191.76277808617536.359495109
2301161.47205846617443.4250188582301098.36402728617250.576531348
#Sta/Elev= 30
       0 3516.18    39.3 3509.72    79.9  3506.3   112.8 3494.14     133 3494.06
   141.1 3496.73   161.3 3498.64   197.6 3479.62   205.7 3477.14   229.9 3465.12
   266.2  3452.2   294.5 3444.12   319.6 3433.22   334.8 3423.77   347.3 3422.89
   367.3 3418.96   380.9 3417.85  387.48 3418.95   401.5 3423.83   418.8 3421.22
   428.7 3427.01   439.8 3430.38   468.8 3437.85   494.5 3442.03   532.2 3457.07
     604 3474.33   616.6 3482.45     625 3492.64   630.5 3495.41   640.4 3497.09
#Mann= 6 ,-1,0
       0     .05       0      50      .1       0  349.71     .06       0
   367.3    .045       0  387.48     .06       0  447.46      .1       0
Bank Sta=367.3,387.48
XS Rating Curve= 0 ,0
Exp/Cntr(USF)=0,0
Exp/Cntr=0.3,0.1

Type RM Length L Ch R = 1 ,464     ,341.6,333.9,323.7
XS GIS Cut Line= 4
2301248.87650348 617878.000249792301360.03183806617553.309667197
2301343.94356595617380.7263845572301218.16252945617295.897313429
#Sta/Elev= 30
       0 3516.29    59.6 3508.12    88.3 3500.27    98.1 3499.92   110.3 3493.83
   127.7 3493.78   144.6 3496.51   157.3 3496.14   211.1  3467.7   237.6 3456.01
   267.2 3447.39   284.1 3439.41   346.9 3427.53   365.2 3416.94   375.5  3413.3
   383.5 3412.18   409.3 3412.88   420.3 3408.19   439.7 3406.95  451.243408.149
   459.8 3412.56   487.9 3411.36     504 3413.28     530 3422.73   559.7  3427.9
   583.8 3434.28   596.7 3441.01   611.1 3454.83   617.6 3458.57   668.2 3466.67
#Mann= 5 ,-1,0
       0      .1       0  373.19     .06       0   420.3    .045       0
  451.24     .06       0  536.52      .1       0
Bank Sta=420.3,451.24
XS Rating Curve= 0 ,0
Exp/Cntr(USF)=0,0
Exp/Cntr=0.3,0.1

Type RM Length L Ch R = 1 ,130     ,,,
XS GIS Cut Line= 4
2301583.80507742617911.6393642032301750.53807929617491.881719139
2301417.07207554617082.3620654172301231.32566118617089.674916377
#Sta/Elev= 30
       0 3516.94    71.5 3493.44    88.7 3482.94   125.1 3466.25   200.6 3437.77
   220.9 3430.56   243.7 3425.51   310.8 3419.39   380.2 3413.42   411.5 3411.03
   441.7 3407.35   503.6 3405.75   511.9 3405.63   525.1 3402.05   571.8 3399.79
   582.1 3397.68   594.4 3396.18  611.993397.701   639.1 3399.67   723.4 3398.35
   753.1  3401.7   782.2 3401.15   791.1 3402.95   813.5 3402.44     913 3401.19
   972.7 3404.34  1016.7 3408.43  1100.8 3421.22  1145.1 3424.35  1165.7 3430.77
#Mann= 12 ,-1,0
       0      .1       0   200.6     .12       0   310.8      .1       0
   380.2     .12       0   411.5    .025       0   503.6      .1       0
   582.1    .045       0  611.99      .1       0   782.2     .06       0
   813.5      .1       0     913     .06       0   972.7      .1       0
Bank Sta=582.1,611.99
XS Rating Curve= 0 ,0
Exp/Cntr(USF)=0,0
Exp/Cntr=0.3,0.1
LCMann Table=0

Chan Stop Cuts=-1
Use User Specified Reach Order=0
Composite Channel Slope=5